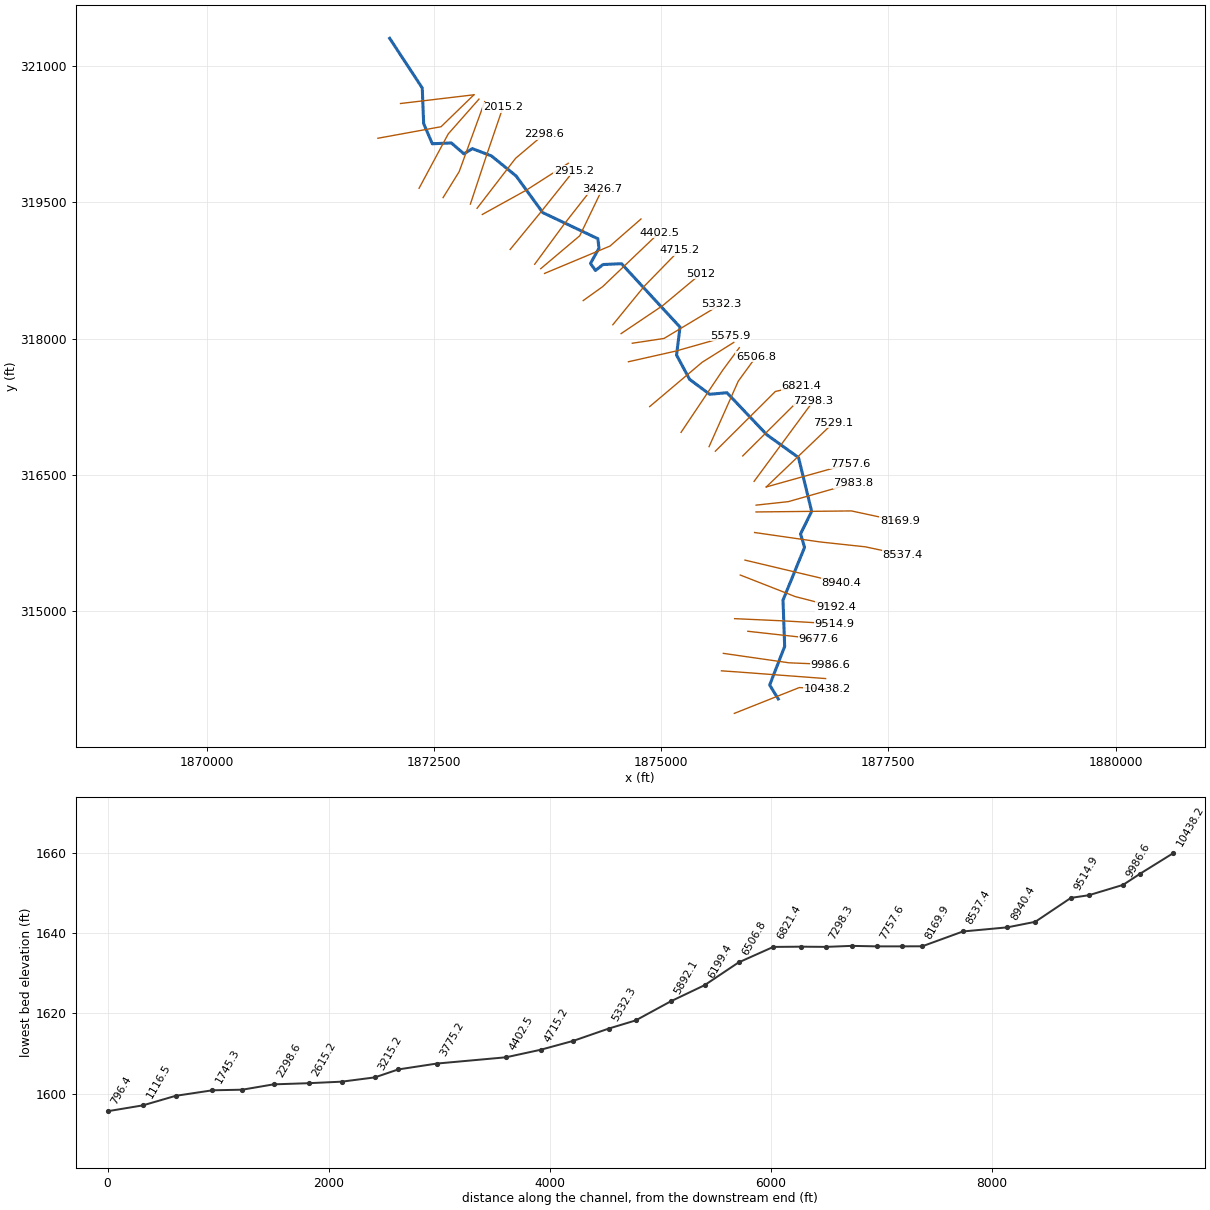
--- ClrFrk2.prj (project) ---

Proj Title=ClrFrk2
Current Plan=p01
Default Exp/Contr=0,0
English Units
Geom File=g01
Flow File=f01
Plan File=p01
BEGIN DESCRIPTION:
END DESCRIPTION:
DSS Export Rating Curves= 0
DSS Export Rating Curve Sorted= 0
DSS Export Volume Flow Curves= 0
DXF OffsetX= 0
DXF OffsetY= 0
DXF ScaleX= 0
DXF ScaleY= 0

--- ClrFrk2.p01 (plan) ---

Plan Title=Floodplain
Program Version=4.00
Geom File=g01
Flow File=f01
K Sum by GR=0
Std Step Tol=0.01
Critical Tol=0.01
Num of Std Step Trials=20
Max Error Tol=0.3
Flow Tol Ratio=0.001
Split Flow NTrial=30
Split Flow Tol=0.02
Split Flow Ratio=0.02
Log Output Level=0
Friction Slope Method=1
Unsteady Friction Slope Method=2
Unsteady Bridges Friction Slope Method=1
Global Log Level=0
CheckData=False
Run HTab=0
Run UNet=0
Run PostProcess=0
UNET Theta=0
UNET Theta Warmup=0
UNET ZTol=0
UNET ZSATol=0
UNET MxIter=0
UNET MaxInSteps=0
UNET DtIC=0
UNET DtMin=0
UNET MaxCRTS=0
UNET WFStab=0
UNET SFStab=0
UNET WFX=0
UNET SFX=0
UNET DSS MLevel=0
UNET DZMax Abort=0
UNET Convert EG Bridges=0
UNET Use Existing IB Tables=0
UNET Froude Limit=0
UNET Froude Power=0
Write IC File=0
Echo Input=False
Echo Output=False
Write Detailed=0

--- ClrFrk2.f01 (steady flow) ---

Flow Title=NFF Regression Equation
Program Version=4.10
Number of Profiles= 1
Profile Names=P100yr
River Rch & RM=ClrFrk2,Main            ,10438.2
906.5707
River Rch & RM=ClrFrk2,Main            ,7983.8
1002.064
River Rch & RM=ClrFrk2,Main            ,7757.6
1318.223
River Rch & RM=ClrFrk2,Main            ,6506.8
1328.105
River Rch & RM=ClrFrk2,Main            ,6199.4
1746.572
River Rch & RM=ClrFrk2,Main            ,5575.9
1757.356
Boundary for River Rch & Prof#=ClrFrk2,Main            , 1
Up Type= 0
Dn Type= 1
Dn Known WS=1600
DSS Import GetInterval= 0
DSS Import GetPeak= 0
DSS Import FillOption= 0

--- ClrFrk2.g01 (geometry) ---

Geom Title=USGS 3m DEM
Program Version=4.10

River Reach=ClrFrk2         ,Main
Reach XY= 30
     1876288.988      314038.667     1876193.886       314191.44
     1876359.011      314615.696     1876340.788      315124.979
      1876577.86      315704.593     1876533.578      315853.081
     1876656.021      316100.555     1876511.456        316691.9
      1876163.69      316941.992     1875724.334      317404.592
      1875533.78      317387.642     1875313.163      317551.589
     1875169.568      317818.851     1875207.673         318126.
     1874564.249       318822.86     1874361.056      318813.748
     1874277.694      318748.624      1874222.99      318825.474
     1874316.775      318993.496     1874303.753      319097.697
     1873698.091      319384.264     1873405.035      319786.748
     1873132.816      320008.181     1872923.113       320087.64
     1872830.633      320030.332      1872692.57      320150.166
     1872482.865      320141.054     1872387.787      320362.483
     1872372.379      320754.332      1872014.04      321299.954

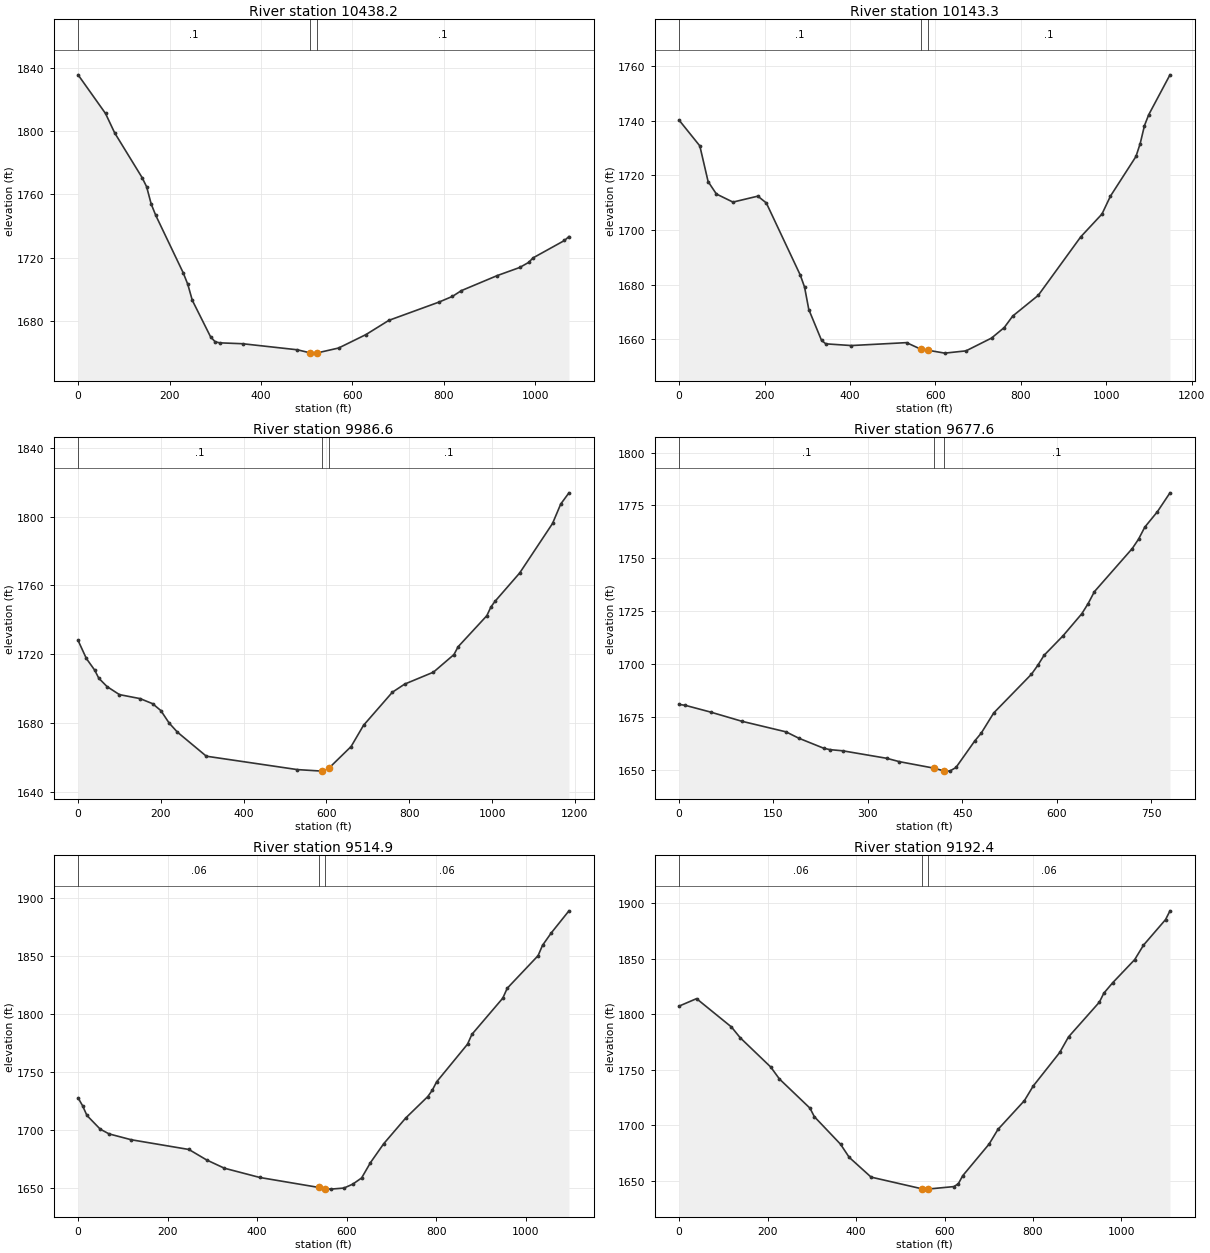
Type RM Length L Ch R = 1 ,10438.2 ,303.5,294.2,284.4
XS GIS Cut Line= 3
     1875805.323      313879.998      1876520.57      314163.913
     1876824.122      314147.504
#Sta/Elev= 30
       0 1835.41      60 1811.02      80  1798.8   139.9 1770.63   149.9  1764.8
   159.9  1753.9   169.9 1746.74   229.9 1710.52   239.9 1703.26   249.8 1693.16
   289.8  1670.1   299.8    1667   309.8 1666.34   359.8 1665.78   479.7 1661.95
   506.7 1660.07   519.7 1659.85   521.7 1659.91   569.7 1663.07   629.6 1671.56
   679.6 1680.52   789.2 1692.04   818.6 1695.63   838.2 1699.27   916.6 1708.76
   965.7 1713.87   985.3 1717.07   995.1 1719.95  1063.7 1730.91  1073.5  1733.4
#Mann= 3 , 0 , 0
       0      .1       0   506.7    .045       0   521.7      .1       0
Bank Sta=506.7,521.7
XS Rating Curve= 0 ,0
Exp/Cntr=0.3,0.1

Type RM Length L Ch R = 1 ,10143.3 ,159.3,156.6,153.8
XS GIS Cut Line= 3
     1875663.365       314347.73     1875847.182       314334.99
      1876809.26      314262.594
#Sta/Elev= 30
       0 1740.31    48.5 1730.86    67.9 1717.76    87.3 1713.21   126.1 1710.24
   184.3 1712.42   204.2 1709.92   283.7 1683.44   293.7 1679.04   303.6 1670.82
   333.4 1659.51   343.4 1658.23   403.1  1657.6   532.4 1658.67   566.8 1656.19
   581.8  1655.9   621.9 1654.82   671.6 1655.65   731.3 1660.34   761.2 1664.22
     781 1668.43   840.7 1676.02   940.2 1697.49   989.9 1705.86  1009.8 1712.45
  1069.5 1726.99  1079.4 1731.74  1089.4 1738.33  1099.3  1742.3  1149.1 1756.94
#Mann= 3 , 0 , 0
       0      .1       0   566.8    .045       0   581.8      .1       0
Bank Sta=566.8,581.8
XS Rating Curve= 0 ,0
Exp/Cntr=0.3,0.1

Type RM Length L Ch R = 1 ,9986.6  ,309,309,309
XS GIS Cut Line= 3
      1875684.75      314539.509     1876406.822      314435.771
     1876862.725      314416.987
#Sta/Elev= 30
       0 1727.99      20 1717.49      40 1710.76      50 1706.03      70 1701.15
    99.9 1696.49   149.9 1694.16   179.9 1691.23   199.9 1687.22   219.8 1680.01
   239.8  1674.7   309.8 1660.68   529.6 1652.89   589.6    1652   590.2 1652.03
   605.2 1653.56   659.5  1666.3   689.5 1678.63   759.2 1697.88     789 1702.61
   858.4 1709.54     908 1719.78     918 1724.31   987.4 1742.38   997.3 1747.46
  1007.2 1750.74  1066.7  1767.2  1146.1 1795.99  1165.9  1807.3  1185.8 1813.82
#Mann= 3 , 0 , 0
       0      .1       0   590.2    .045       0   605.2      .1       0
Bank Sta=590.2,605.2
XS Rating Curve= 0 ,0
Exp/Cntr=0.3,0.1

Type RM Length L Ch R = 1 ,9677.6  ,160.7,162.7,164.4
XS GIS Cut Line= 2
      1875953.65      314782.474     1876728.956      314696.481
#Sta/Elev= 30
       0 1680.96      10 1680.52      50 1677.35     100 1672.98     170 1667.99
     190 1665.02     230 1660.23     240 1659.58     260 1659.04     330 1655.49
     350 1653.91   405.6  1650.8   420.6 1649.54     430 1649.43     440 1651.15
     470 1663.77     480 1667.33     500 1676.94     560 1695.26     570 1699.44
     580 1704.18     610 1713.36     640 1723.85     650 1728.62     660 1734.28
   720.1 1754.64   730.1 1759.06   740.1 1764.79   760.1 1772.07   780.1 1780.99
#Mann= 3 , 0 , 0
       0      .1       0   405.6    .045       0   420.6      .1       0
Bank Sta=405.6,420.6
XS Rating Curve= 0 ,0
Exp/Cntr=0.3,0.1

Type RM Length L Ch R = 1 ,9514.9  ,331,322.5,314
XS GIS Cut Line= 3
     1875808.585      314921.138     1876352.949       314896.38
     1876904.112      314864.483
#Sta/Elev= 30
       0 1727.57     9.9 1720.95    19.8 1712.41    49.5 1700.58    69.4 1696.47
   118.9 1691.42   247.7 1683.02   287.3 1673.97     327 1666.83   406.2 1658.82
   537.4 1650.25   552.4 1649.19   564.6 1648.76   594.2 1649.69   613.9 1653.08
   633.6 1658.41   653.4 1671.66     683    1688   732.2 1710.22   781.5 1728.74
   791.4 1734.12   801.2 1741.43   870.3 1774.02   880.1  1782.5   949.1 1813.78
     959 1822.32    1028 1850.51  1037.9 1859.44  1057.6 1870.24    1097 1889.25
#Mann= 3 , 0 , 0
       0     .06       0   537.4    .045       0   552.4     .06       0
Bank Sta=537.4,552.4
XS Rating Curve= 0 ,0
Exp/Cntr=0.3,0.1

Type RM Length L Ch R = 1 ,9192.4  ,248.8,252,255.1
XS GIS Cut Line= 3
     1875870.387      315400.808     1876476.435      315163.303
     1876920.807      315049.413
#Sta/Elev= 30
       0 1807.33    39.4 1814.03   118.4 1788.53   138.1 1778.89   207.1 1752.57
   226.8 1741.81   295.9 1715.56   305.7 1707.94   364.9 1683.19   384.6 1671.36
     434  1653.6   548.1 1643.17   552.3  1642.8   563.1 1642.87   621.3 1645.09
   631.2 1647.62   641.1 1654.84   700.8 1683.32   720.7 1696.42   780.6 1722.37
   800.5 1735.48   860.4 1765.62   880.3 1779.62   950.1  1810.9   960.1 1818.91
     980 1828.25  1029.9  1849.1  1049.8 1862.09  1099.7  1885.1  1109.7 1892.97
#Mann= 3 , 0 , 0
       0     .06       0   548.1    .045       0   563.1     .06       0
Bank Sta=548.1,563.1
XS Rating Curve= 0 ,0
Exp/Cntr=0.3,0.1

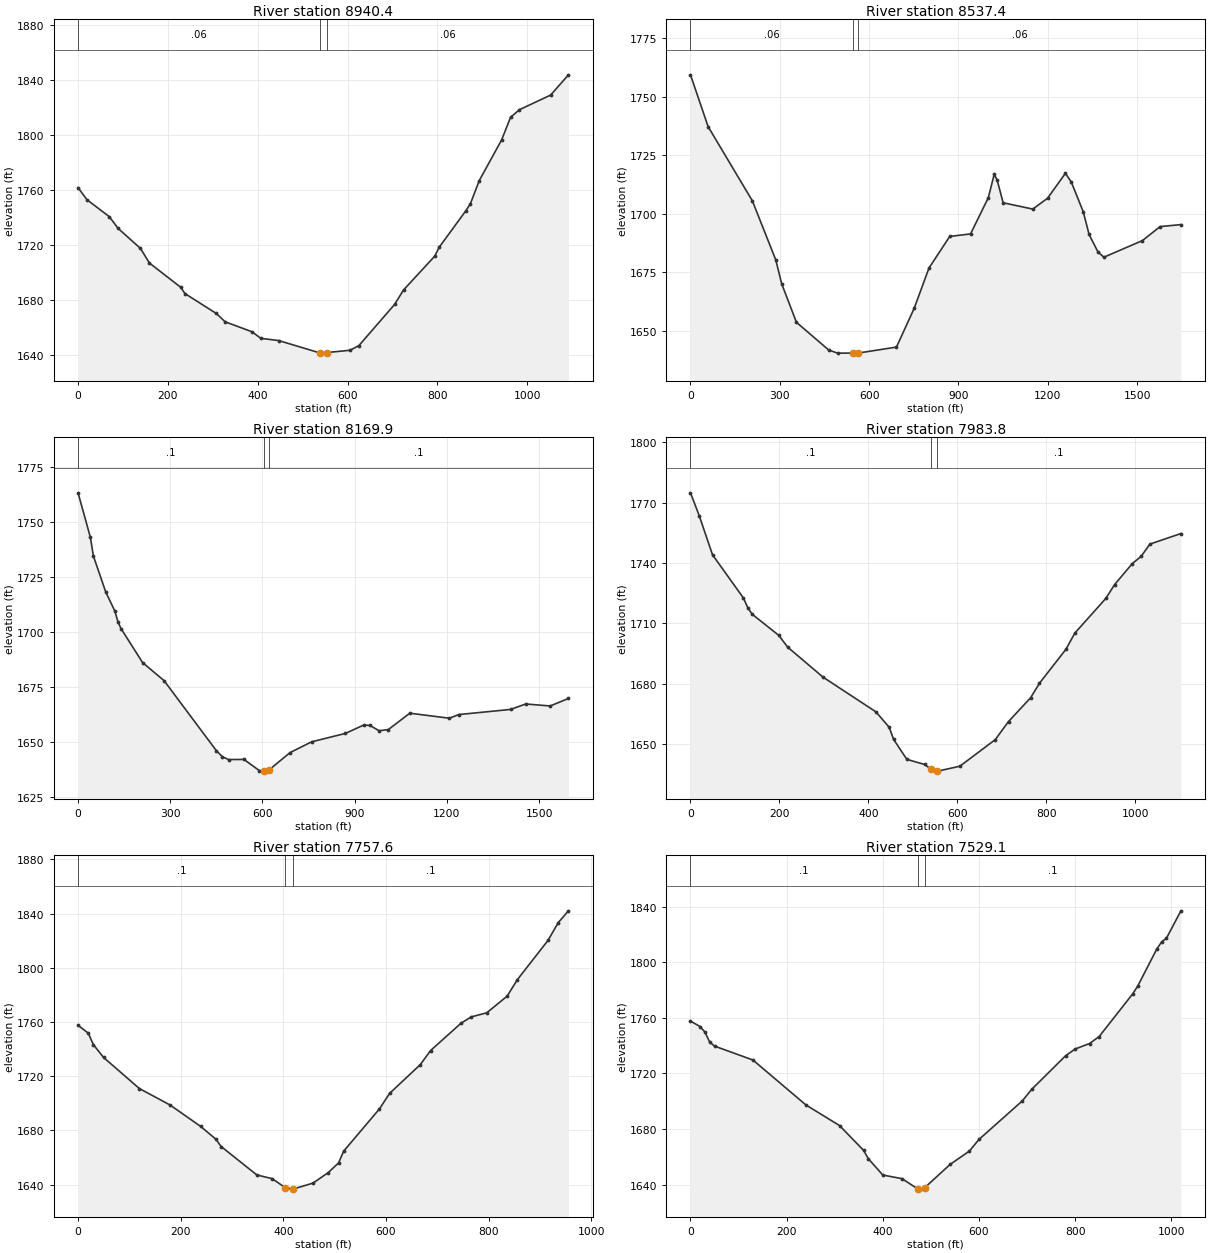
Type RM Length L Ch R = 1 ,8940.4  ,413.2,402.9,403.7
XS GIS Cut Line= 2
     1875922.603      315564.555     1876985.166      315312.714
#Sta/Elev= 30
       0 1761.71    19.8 1752.99    69.5 1740.65    89.4 1732.04     139 1717.54
   158.8 1706.95   228.3 1689.36   238.2 1684.67   307.8 1670.27   327.6 1664.18
   387.2 1656.96     407 1652.17   446.7 1650.56   538.5 1641.56     546 1641.42
   553.5 1641.84   605.6 1643.49   625.4 1646.92   704.8 1676.81   724.7 1687.32
   794.2 1711.94   804.1 1718.39   863.7 1745.04   873.6 1750.02   893.4 1766.91
   943.1 1796.42     963 1812.86   982.8  1818.4  1052.3 1829.05    1092 1843.76
#Mann= 3 , 0 , 0
       0     .06       0   538.5    .045       0   553.5     .06       0
Bank Sta=538.5,553.5
XS Rating Curve= 0 ,0
Exp/Cntr=0.3,0.1

Type RM Length L Ch R = 1 ,8537.4  ,352.2,367.5,371.3
XS GIS Cut Line= 4
     1876028.238      315868.003      1876752.16      315763.892
     1877247.338      315710.527     1877655.774      315623.299
#Sta/Elev= 30
       0 1759.35    59.3 1737.19   207.6 1705.54   286.6 1680.19   306.4    1670
   355.8 1653.57   464.5  1641.7   494.2 1640.39   547.4  1640.4   562.4  1640.4
   691.8 1642.97   751.3 1659.53   801.1 1676.79   870.8 1690.28   940.6 1691.34
  1000.3 1706.82  1020.2 1716.85  1030.2 1714.29  1050.1 1704.66  1149.7 1701.96
  1199.5 1706.63  1259.2 1717.26  1279.1 1713.51  1318.9  1700.9  1338.8 1691.12
  1368.6 1683.62  1388.5 1681.39  1517.8 1688.49  1577.4 1694.48  1647.1 1695.33
#Mann= 3 , 0 , 0
       0     .06       0   547.4    .045       0   562.4     .06       0
Bank Sta=547.4,562.4
XS Rating Curve= 0 ,0
Exp/Cntr=0.3,0.1

Type RM Length L Ch R = 1 ,8169.9  ,181.8,185.9,192.7
XS GIS Cut Line= 3
     1876043.787      316093.962     1877093.402      316105.319
      1877627.11      315990.478
#Sta/Elev= 30
       0 1763.25      40 1743.04      50 1734.48      90 1718.19     120 1709.39
     130 1704.47     140 1701.46   209.9 1686.07   279.9 1677.84   449.9 1646.01
   469.9 1643.19   489.8 1641.96   539.8 1642.01   589.8 1636.94   604.8  1636.7
   619.8 1637.08   689.8 1645.13   759.8 1650.02   869.7 1653.84   929.7 1657.67
   949.7 1657.46   979.7 1655.06  1009.7 1655.61  1079.4 1663.04  1208.5 1660.75
  1238.3 1662.42    1407 1664.75  1456.6 1667.23    1536 1666.33  1595.6 1669.74
#Mann= 3 , 0 , 0
       0      .1       0   604.8    .045       0   619.8      .1       0
Bank Sta=604.8,619.8
XS Rating Curve= 0 ,0
Exp/Cntr=0.3,0.1

Type RM Length L Ch R = 1 ,7983.8  ,226.7,226.2,225.8
XS GIS Cut Line= 3
     1876044.745      316168.885     1876399.997      316207.509
     1877116.964      316411.255
#Sta/Elev= 30
       0 1774.83    19.8 1763.39    49.6 1744.04   119.1  1722.6     129 1717.73
     139 1714.52   198.5 1704.09   218.4 1698.26   297.8 1683.38     417  1666.1
   446.8 1658.45   456.7 1652.45   486.5 1642.52   526.3 1639.99   539.8 1637.85
   554.8 1636.72   556.1 1636.68   605.8 1639.13   685.3 1652.31   715.1  1661.3
   764.8  1673.1   784.7 1680.32   844.3 1697.18   864.2  1705.2   933.8 1722.38
   953.6 1729.26   993.4  1739.7  1013.3  1743.3  1033.1 1749.38  1102.7 1754.62
#Mann= 3 , 0 , 0
       0      .1       0   539.8    .045       0   554.8      .1       0
Bank Sta=539.8,554.8
XS Rating Curve= 0 ,0
Exp/Cntr=0.3,0.1

Type RM Length L Ch R = 1 ,7757.6  ,217.3,228.5,239.7
XS GIS Cut Line= 2
     1876156.608      316368.829     1877077.073      316626.299
#Sta/Elev= 30
       0 1757.59    19.9 1751.82    29.9 1743.29    49.8 1733.84   119.5 1710.92
   179.2 1698.81     239 1682.95   268.8 1673.46   278.8 1668.14   348.5 1647.13
   378.3 1644.41     404 1637.73   418.2 1636.68     419 1636.71     458 1641.14
   487.8 1648.95   507.8 1656.08   517.7 1664.72   587.4  1695.9   607.3  1707.4
   667.1 1728.61     687 1738.96   746.7 1759.24   766.6 1763.83   796.5 1766.82
   836.3 1779.12   856.2  1791.3     916 1820.32   935.9  1833.4   955.8 1842.09
#Mann= 3 , 0 , 0
       0      .1       0     404    .045       0     419      .1       0
Bank Sta=404,419
XS Rating Curve= 0 ,0
Exp/Cntr=0.3,0.1

Type RM Length L Ch R = 1 ,7529.1  ,227.9,230.8,234
XS GIS Cut Line= 2
     1876156.608      316368.829     1876894.003      317073.307
#Sta/Elev= 30
       0 1757.59      20 1753.69      30 1749.72      40  1742.5      50 1739.64
     130  1729.6     240 1697.34     310 1682.49   359.9 1664.68   369.9 1658.65
   399.9 1646.95   439.9 1644.32   472.4    1637   479.9  1636.8   487.4 1637.92
   539.9 1654.58   579.9 1664.12   599.9 1672.52   689.9  1700.2   709.9 1708.66
   779.9 1732.64   799.9 1737.54   829.9 1741.49   849.8 1746.48   919.8 1777.28
   929.8 1782.64   969.8 1809.52   979.8 1814.56   989.8 1817.22  1019.8 1836.89
#Mann= 3 , 0 , 0
       0      .1       0   472.4    .045       0   487.4      .1       0
Bank Sta=472.4,487.4
XS Rating Curve= 0 ,0
Exp/Cntr=0.3,0.1

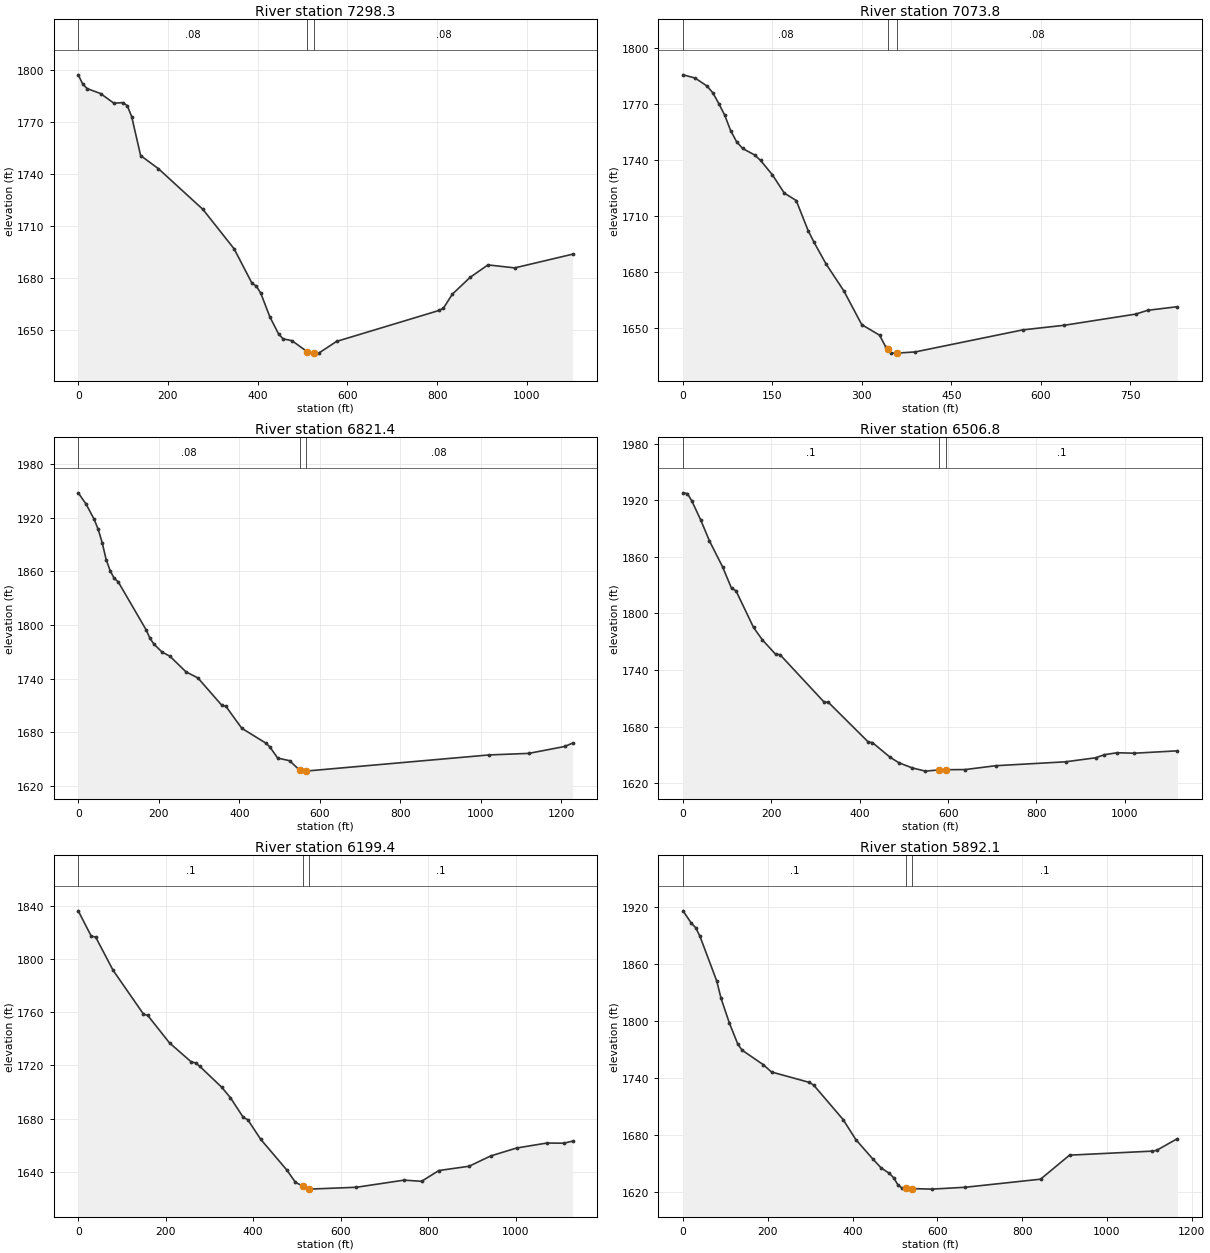
Type RM Length L Ch R = 1 ,7298.3  ,227.6,224.5,221.1
XS GIS Cut Line= 2
     1876022.872      316430.448     1876676.947      317316.977
#Sta/Elev= 30
       0 1797.29     9.9    1792    19.8 1789.33    49.6  1786.5    79.4  1780.9
    99.2 1781.23   109.2 1779.52   119.1 1773.11     139 1750.67   178.6 1743.09
   277.9 1719.56   347.4 1696.78   387.1 1676.98     397 1675.22   406.9  1671.1
   426.8 1657.62   446.6 1647.56   456.6 1644.78   476.4 1643.73   510.9 1637.26
   525.9  1636.6     536 1636.55   575.7 1643.32   803.9 1661.18   813.9 1662.54
   833.7 1670.59   873.4 1680.33   913.1 1687.51   972.7 1685.78  1101.7 1693.69
#Mann= 3 , 0 , 0
       0     .08       0   510.9    .045       0   525.9     .08       0
Bank Sta=510.9,525.9
XS Rating Curve= 0 ,0
Exp/Cntr=0.3,0.1

Type RM Length L Ch R = 1 ,7073.8  ,252.3,252.4,252.4
XS GIS Cut Line= 2
     1875897.686      316709.819      1876485.99      317294.029
#Sta/Elev= 30
       0 1785.65      20 1783.96      40  1779.7      50 1775.98    59.9 1770.28
    69.9 1764.01    79.9  1755.7    89.9 1749.76    99.9  1746.2   119.9 1742.76
   129.9 1739.86   149.8  1732.1   169.8 1722.31   189.8 1718.34   209.8 1702.22
   219.8 1695.91   239.7 1684.43   269.7 1669.93   299.7 1651.86   329.6 1646.21
   339.6 1640.12   343.8 1638.65   349.6 1636.63   358.8  1636.6   389.6 1637.26
   569.4 1649.03   639.3 1651.52   759.2  1657.5   779.2 1659.53   829.1 1661.46
#Mann= 3 , 0 , 0
       0     .08       0   343.8    .045       0   358.8     .08       0
Bank Sta=343.8,358.8
XS Rating Curve= 0 ,0
Exp/Cntr=0.3,0.1

Type RM Length L Ch R = 1 ,6821.4  ,305.2,314.4,323.5
XS GIS Cut Line= 3
      1875596.39      316761.656     1876256.674      317418.242
     1876546.049       317483.76
#Sta/Elev= 30
       0  1947.9    19.8 1935.02    39.6 1918.15    49.5 1907.07    59.4 1892.21
    69.3  1873.2    79.2 1860.82    89.2 1852.23    99.1 1848.43   168.4 1794.79
   178.3 1784.98   188.2 1778.53     208  1769.8   227.8 1765.04   267.5 1747.63
   297.2 1740.82   356.6  1710.2   366.5 1709.19   406.2 1684.49   465.6 1667.99
   475.5 1663.87   495.3 1651.17     525  1648.2   550.3 1637.43   554.7 1636.54
   565.3 1636.59  1020.2 1654.65  1119.1  1656.4  1208.1 1664.11  1227.9 1667.87
#Mann= 3 , 0 , 0
       0     .08       0   550.3    .045       0   565.3     .08       0
Bank Sta=550.3,565.3
XS Rating Curve= 0 ,0
Exp/Cntr=0.3,0.1

Type RM Length L Ch R = 1 ,6506.8  ,311.2,307.6,303.8
XS GIS Cut Line= 3
     1875527.543      316811.876     1875848.547      317531.535
     1876043.576       317799.18
#Sta/Elev= 30
       0 1927.87      10 1927.03      20 1919.11    39.9 1899.14    59.8 1876.86
    89.8 1849.01   109.7 1826.63   119.7  1824.1   159.6 1785.06   179.6 1771.89
   209.5 1756.65   219.4 1756.26   319.2 1705.98   329.2 1705.56   418.9 1663.77
   428.9 1662.86   468.8 1647.39   488.8 1641.52   518.7 1636.11   548.6 1632.67
     580 1633.97     595 1634.19   638.4 1634.32   708.2 1638.43   865.9 1642.56
   934.1 1646.81   953.6 1650.07   982.8 1652.17  1021.8 1651.68  1119.2  1654.2
#Mann= 3 , 0 , 0
       0      .1       0     580    .045       0     595      .1       0
Bank Sta=580,595
XS Rating Curve= 0 ,0
Exp/Cntr=0.3,0.1

Type RM Length L Ch R = 1 ,6199.4  ,313.7,307.3,300.7
XS GIS Cut Line= 3
     1875219.367      316969.121     1875678.578      317653.822
     1875860.265      317899.527
#Sta/Elev= 30
       0 1836.11    29.8    1817    39.7 1816.47    79.5  1791.5     149 1758.56
   158.9  1757.5   208.6 1736.87   258.3  1722.6   268.2  1721.9   278.1 1719.17
   327.8 1703.62   347.6  1695.8   377.4 1680.84   387.4 1679.21   417.2 1664.39
   476.8 1641.35   496.6 1632.08   513.2 1629.33   526.4    1627   528.2 1627.01
   635.7  1628.4     745 1633.77   784.7 1632.86   824.4 1640.98   893.4 1644.19
   942.7 1651.92  1001.9 1657.88  1070.9 1661.62  1110.3 1661.52    1130 1663.08
#Mann= 3 , 0 , 0
       0      .1       0   513.2    .045       0   528.2      .1       0
Bank Sta=513.2,528.2
XS Rating Curve= 0 ,0
Exp/Cntr=0.3,0.1

Type RM Length L Ch R = 1 ,5892.1  ,322.2,316.2,308
XS GIS Cut Line= 3
      1874874.22      317252.254     1875451.441      317739.409
     1875799.491      317957.696
#Sta/Elev= 30
       0 1915.75    19.9 1902.46    29.8 1898.07    39.8 1888.99    79.5  1841.9
    89.4 1824.02   109.3 1797.64   129.2 1775.46   139.1 1769.21   188.8 1754.03
   208.7  1746.2   298.2 1735.21   308.1 1732.42   377.7 1696.11   407.5 1675.15
   447.2 1654.92   467.1 1645.36     487 1639.44   496.9 1634.89   506.9 1627.51
   516.8 1623.94     525 1623.72     540 1623.54   586.4 1622.96   665.9 1624.93
   843.4 1633.43   911.8  1658.7  1107.5 1662.96  1117.2 1663.76  1166.2 1676.05
#Mann= 3 , 0 , 0
       0      .1       0     525    .045       0     540      .1       0
Bank Sta=525,540
XS Rating Curve= 0 ,0
Exp/Cntr=0.3,0.1

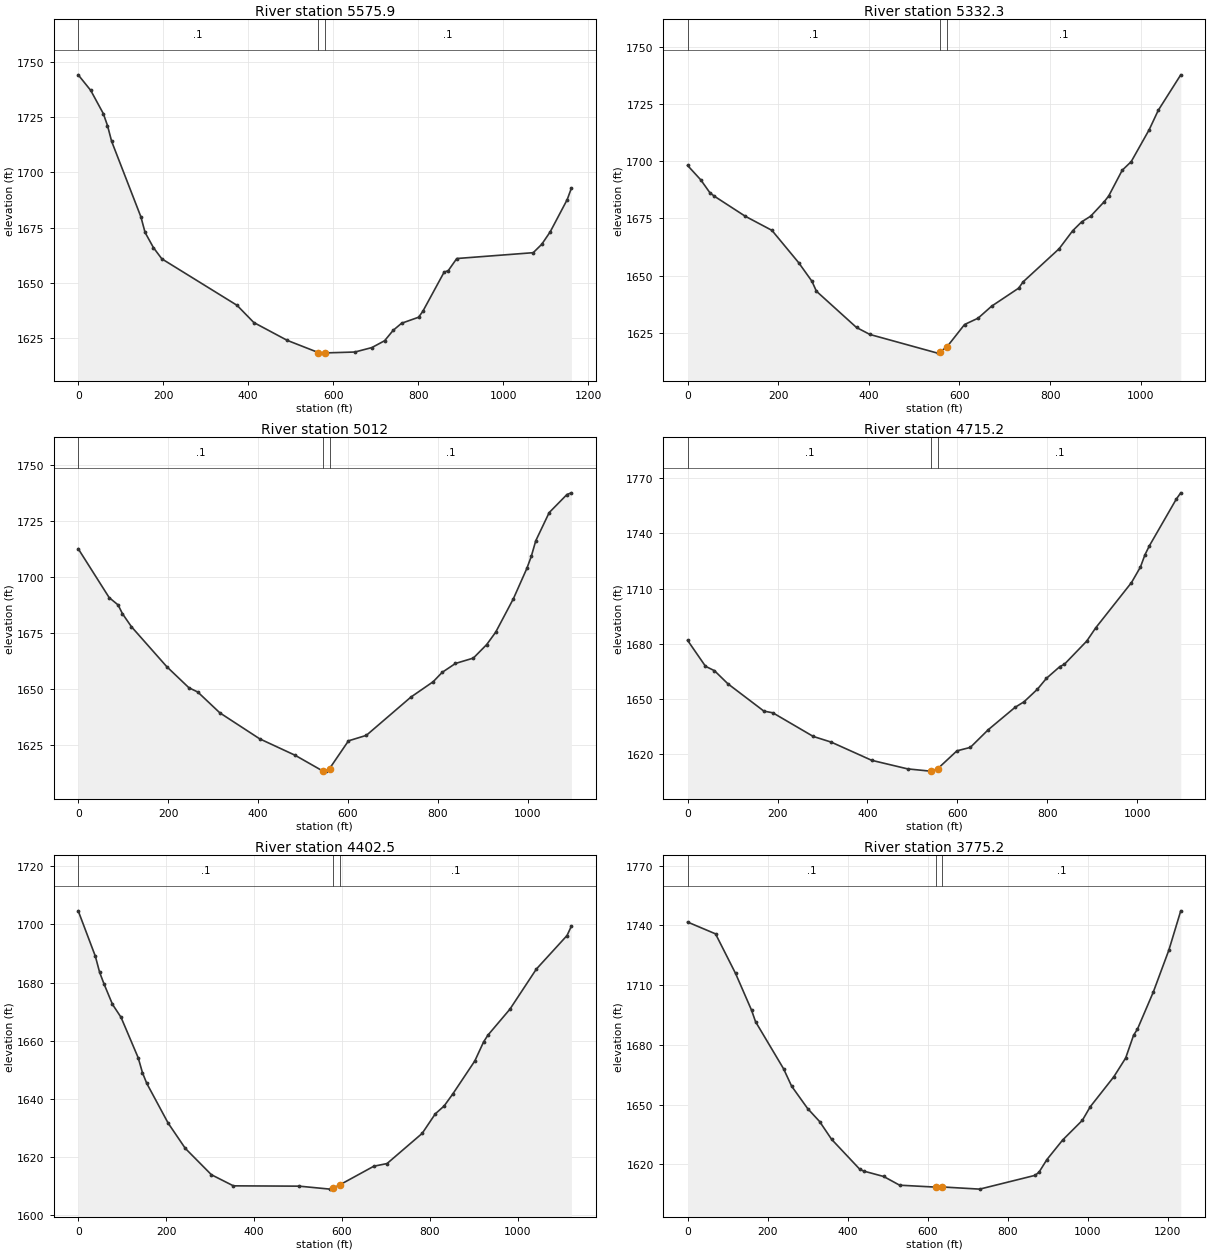
Type RM Length L Ch R = 1 ,5575.9  ,241.4,243.4,247.5
XS GIS Cut Line= 3
     1874640.622      317744.995     1875158.889       317861.65
     1875764.538      318033.171
#Sta/Elev= 30
       0 1744.01    29.5 1736.96      59 1726.52    68.9 1721.09    78.7 1713.93
   147.6 1679.79   157.4 1672.75   177.1  1665.9   196.8 1660.84   373.8 1639.83
   413.2 1632.06   491.9 1623.99   564.9  1618.5   571.2 1618.22   579.9 1618.31
   651.1 1618.72   691.1 1620.73   721.1 1623.83   741.1  1628.5     761 1631.72
     801 1634.44     811 1637.12     861 1654.78     871 1655.55   890.9 1660.98
  1070.8 1663.62  1090.8  1667.4  1110.7 1673.02  1150.7 1687.58  1160.7 1692.81
#Mann= 3 , 0 , 0
       0      .1       0   564.9    .045       0   579.9      .1       0
Bank Sta=564.9,579.9
XS Rating Curve= 0 ,0
Exp/Cntr=0.3,0.1

Type RM Length L Ch R = 1 ,5332.3  ,319.2,320.3,323.8
XS GIS Cut Line= 3
     1874682.798      317948.441     1875031.733       318001.11
     1875662.119      318379.671
#Sta/Elev= 30
       0 1698.12    29.4 1691.76      49 1686.28    58.8 1684.72   127.4 1675.93
   186.2 1669.77   245.1 1655.69   274.5 1647.55   284.3 1643.22   372.8 1627.38
   402.6 1624.32   551.6 1616.19   557.1 1616.79   572.1 1618.86   611.2 1628.68
     641 1631.44   670.9 1636.68   730.5 1644.54   740.4  1647.3   819.9 1661.76
   849.7 1669.59   869.6 1673.49   889.5 1675.96   919.3 1682.27   929.2 1684.77
     959    1696   978.9 1699.77  1018.6 1713.72  1038.5 1722.14  1088.2 1737.65
#Mann= 3 , 0 , 0
       0      .1       0   557.1    .045       0   572.1      .1       0
Bank Sta=557.1,572.1
XS Rating Curve= 0 ,0
Exp/Cntr=0.3,0.1

Type RM Length L Ch R = 1 ,5012    ,290.1,296.8,299.2
XS GIS Cut Line= 3
     1874559.639      318054.277     1875017.205      318362.011
     1875435.834      318711.644
#Sta/Elev= 30
       0 1712.58    68.9 1690.71    88.6 1687.46    98.5 1683.49   118.2 1677.75
   196.9 1659.85   246.2 1650.41   265.9  1648.5   315.1 1639.17   403.7 1627.56
   482.5 1620.21   543.9 1613.18   551.4 1613.13   558.9 1614.26     601 1626.67
   640.7 1629.12   739.8 1646.23   789.4 1653.11   809.3 1657.28     839 1661.28
   878.7 1663.67   908.4 1669.72   928.3 1675.23   967.9 1690.28   997.7 1703.78
  1007.6 1709.19  1017.5 1716.13  1047.3 1728.72  1086.9 1736.82  1096.8 1737.57
#Mann= 3 , 0 , 0
       0      .1       0   543.9    .045       0   558.9      .1       0
Bank Sta=543.9,558.9
XS Rating Curve= 0 ,0
Exp/Cntr=0.3,0.1

Type RM Length L Ch R = 1 ,4715.2  ,315.5,312.6,311.8
XS GIS Cut Line= 3
     1874468.942      318151.971     1874816.286      318577.185
     1875198.659      318968.825
#Sta/Elev= 30
       0 1681.98    39.9 1667.86    59.9 1665.45    89.8 1658.33   169.7 1643.51
   189.7 1642.57   279.5 1629.74   319.4 1626.66   409.3 1616.78   489.2 1612.12
   539.1  1610.9   541.5 1610.98   556.5 1612.29   598.8 1621.91   628.7  1623.8
   668.5  1633.4   728.2 1645.58   748.1 1648.58   777.9 1655.43   797.8 1661.31
   827.7  1667.7   837.6 1668.91   887.4 1681.54   907.3 1688.71   986.9 1713.34
  1006.8 1721.78  1016.8 1728.42  1026.7 1733.32  1086.4 1758.64  1096.4 1762.08
#Mann= 3 , 0 , 0
       0      .1       0   541.5    .045       0   556.5      .1       0
Bank Sta=541.5,556.5
XS Rating Curve= 0 ,0
Exp/Cntr=0.3,0.1

Type RM Length L Ch R = 1 ,4402.5  ,634.9,627.9,621.8
XS GIS Cut Line= 3
     1874142.938      318417.527     1874356.907      318570.597
     1874978.433      319163.244
#Sta/Elev= 30
       0  1704.7      39 1689.09    48.7 1683.58    58.5 1679.65      78 1672.55
    97.4  1668.1   136.4 1654.21   146.2 1649.05   155.9  1645.4   204.6 1631.72
   243.6 1623.04     303 1613.98     353 1610.16   502.8 1610.05   572.6 1609.03
   580.7 1609.34   595.7 1610.56   672.5 1616.91   702.5 1617.82   782.4 1628.19
   812.3 1634.92   832.3  1637.6   852.3  1641.8   902.2 1653.11   922.2 1659.66
   932.1 1661.99   982.1 1670.91    1042 1684.65  1111.9 1696.21  1121.9 1699.46
#Mann= 3 , 0 , 0
       0      .1       0   580.7    .045       0   595.7      .1       0
Bank Sta=580.7,595.7
XS Rating Curve= 0 ,0
Exp/Cntr=0.3,0.1

Type RM Length L Ch R = 1 ,3775.2  ,334.7,347.8,359.1
XS GIS Cut Line= 3
     1873717.671      318715.889     1874437.557       319016.64
     1874778.544      319314.187
#Sta/Elev= 30
       0 1741.73      70 1735.78     120 1715.89     160  1697.4     170 1691.62
   240.1 1667.93   260.1 1659.24   300.1 1647.99   330.1 1641.44   360.1 1632.49
   430.1 1617.53   440.1 1616.54   490.1 1613.82   530.1 1609.44   622.2 1608.45
   637.2 1608.54   730.2 1607.46   868.7 1614.39   878.6 1616.02   898.2 1622.33
   937.6 1632.17   986.8 1642.06  1006.5 1648.87  1065.5 1663.96    1095 1673.36
  1114.7 1684.77  1124.5 1687.91  1163.9 1706.44  1203.2 1727.75  1232.7 1747.36
#Mann= 3 , 0 , 0
       0      .1       0   622.2    .045       0   637.2      .1       0
Bank Sta=622.2,637.2
XS Rating Curve= 0 ,0
Exp/Cntr=0.3,0.1

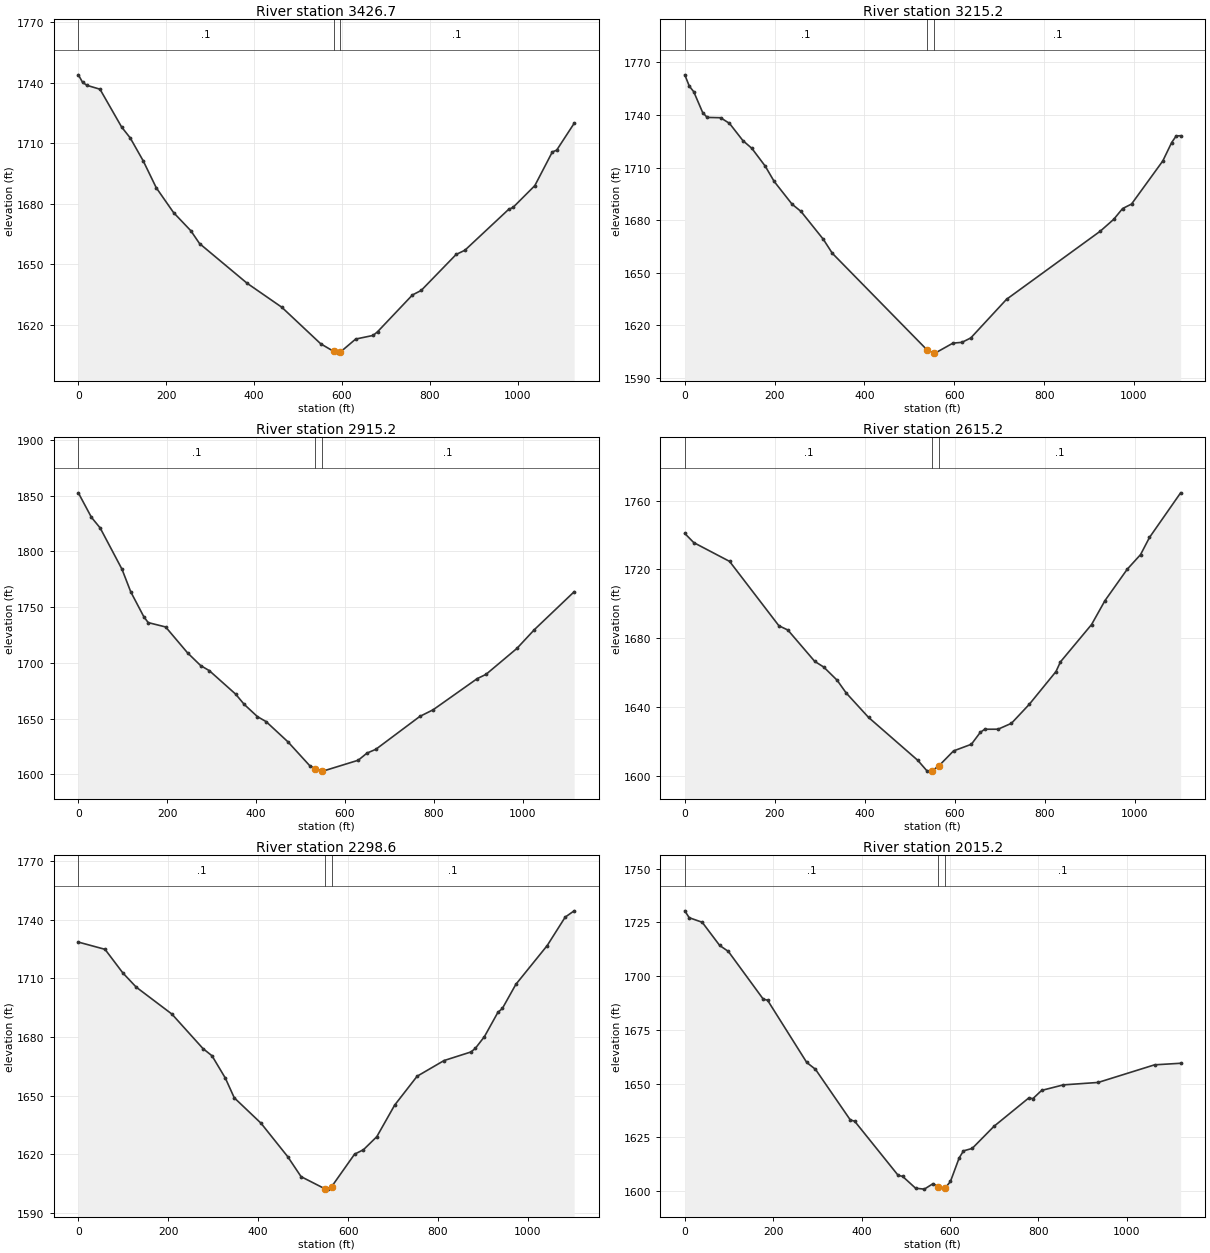
Type RM Length L Ch R = 1 ,3426.7  ,215.6,211.5,207
XS GIS Cut Line= 3
     1873675.806      318767.941     1874105.082      319130.209
     1874351.888      319640.646
#Sta/Elev= 30
       0 1743.95     9.8  1740.2    19.7 1738.73    49.3 1736.82    98.6 1718.06
   118.2 1712.65   147.8 1701.26   177.4 1687.97   216.8 1675.66   256.2 1666.64
   275.9 1660.32   384.3 1640.62   463.2 1628.74   551.8 1610.62   580.9 1606.91
   591.6    1606   595.9 1606.43   631.3 1612.97   671.1 1614.78   681.1 1616.58
   760.6 1634.84   780.5 1637.07   860.1 1654.92     880    1657   979.5 1677.25
   989.4 1678.19  1039.2 1689.04    1079 1705.72  1088.9  1706.6  1128.7 1719.92
#Mann= 3 , 0 , 0
       0      .1       0   580.9    .045       0   595.9      .1       0
Bank Sta=580.9,595.9
XS Rating Curve= 0 ,0
Exp/Cntr=0.3,0.1

Type RM Length L Ch R = 1 ,3215.2  ,301.7,300,298.9
XS GIS Cut Line= 3
     1873609.059      318816.511     1873933.252      319257.455
     1874276.855      319695.231
#Sta/Elev= 30
       0 1762.91      10 1756.46    19.9 1753.27    39.8 1741.37    49.8  1738.6
    79.6 1738.42    99.5 1735.19   129.4 1725.34   149.3 1720.93   179.1 1710.76
     199 1702.03   238.8 1689.06   258.7 1684.91   308.5 1668.97   328.4 1661.03
   539.8 1605.73   554.8 1604.06   557.2 1604.02     597 1609.74   616.9 1610.17
   636.7  1612.7   716.2 1634.74   924.9 1673.64   954.8  1680.4   974.6 1686.56
   994.5 1689.13  1064.1 1713.74  1083.9 1724.27  1093.9 1728.02  1103.8 1728.14
#Mann= 3 , 0 , 0
       0      .1       0   539.8    .045       0   554.8      .1       0
Bank Sta=539.8,554.8
XS Rating Curve= 0 ,0
Exp/Cntr=0.3,0.1

Type RM Length L Ch R = 1 ,2915.2  ,308.3,300,292.7
XS GIS Cut Line= 3
     1873339.253       318979.17     1873682.443      319397.113
     1874041.414      319846.947
#Sta/Elev= 30
       0  1852.6    29.5 1830.63    49.2 1821.06    98.3 1784.07     118  1763.8
   147.5  1741.4   157.3 1736.19   196.6 1732.27   245.8  1709.1   275.3 1697.67
     295 1693.05     354 1672.09   373.6 1662.77   403.1 1651.88   422.8 1647.36
     472  1629.2   521.1 1607.77   533.3 1605.14   548.3 1603.23   550.7 1602.95
   630.1 1612.71   649.9 1619.12   669.8 1622.52     769 1652.07   798.8 1657.98
     898 1685.92   917.8 1689.73   987.3 1712.99    1027 1729.97  1116.3 1763.86
#Mann= 3 , 0 , 0
       0      .1       0   533.3    .045       0   548.3      .1       0
Bank Sta=533.3,548.3
XS Rating Curve= 0 ,0
Exp/Cntr=0.3,0.1

Type RM Length L Ch R = 1 ,2615.2  ,307.4,316.6,324.4
XS GIS Cut Line= 3
     1873032.904      319363.877     1873520.888      319633.362
      1873978.86      319926.919
#Sta/Elev= 30
       0 1740.88    19.9 1735.55    99.5 1724.62     209 1687.17     229 1684.67
   288.7 1666.42   308.6 1663.14   338.4 1655.46   358.4 1648.08   408.1 1633.85
   517.6 1608.84   537.5 1602.86   547.5 1602.57     550 1602.87     565  1605.8
     597 1614.34   636.6  1618.2   656.4 1625.13   666.2 1626.94   695.9 1626.97
   725.6  1630.4   765.2 1641.44   824.5  1660.5   834.4 1666.13   903.6 1687.88
   933.3 1701.78   982.7 1720.03  1012.4 1728.57  1032.2 1738.54  1101.4 1764.52
#Mann= 3 , 0 , 0
       0      .1       0     550    .045       0     565      .1       0
Bank Sta=550,565
XS Rating Curve= 0 ,0
Exp/Cntr=0.3,0.1

Type RM Length L Ch R = 1 ,2298.6  ,275.6,283.3,290.7
XS GIS Cut Line= 3
     1872975.485      319431.819     1873398.984      319981.147
     1873711.465      320245.343
#Sta/Elev= 30
       0 1728.51    59.4  1724.8    99.1 1712.72   128.8 1705.48   208.1 1691.73
   277.4 1674.06   297.3 1670.42     327    1659   346.8 1648.95   406.3 1635.96
   465.7 1618.87   495.4 1608.66   548.1 1602.49   554.9 1602.28   563.1 1603.45
   614.4 1620.14   634.2 1622.42   663.9 1629.09   703.6 1645.22   753.5 1659.96
   813.4 1667.98   873.3 1672.37   883.2 1674.26   903.2  1680.2   933.2 1692.61
   943.1 1694.59   973.1  1706.9  1042.9 1726.75  1082.9 1741.27  1102.8 1744.48
#Mann= 3 , 0 , 0
       0      .1       0   548.1    .045       0   563.1      .1       0
Bank Sta=548.1,563.1
XS Rating Curve= 0 ,0
Exp/Cntr=0.3,0.1

Type RM Length L Ch R = 1 ,2015.2  ,270.5,269.9,263.3
XS GIS Cut Line= 3
     1872901.945      319478.016     1873084.913      320030.041
     1873259.926      320541.459
#Sta/Elev= 30
       0 1730.37     9.9 1727.18    39.4 1725.05    78.9 1714.28    98.6 1711.48
   177.4 1689.34   187.3  1688.8     276 1659.84   295.7 1656.68   374.6 1633.11
   384.4 1632.54     483 1607.32   492.8  1606.9   522.4 1601.36   542.1 1600.95
   561.8 1603.49   574.1 1602.04   589.1 1601.46   601.2 1604.52   620.9 1615.45
   630.7 1618.74   650.4 1619.88   699.5 1630.12   778.1 1643.29   787.9 1643.06
   807.6 1646.86   856.7 1649.43   935.4 1650.56  1063.1 1658.75  1122.1 1659.48
#Mann= 3 , 0 , 0
       0      .1       0   574.1    .045       0   589.1      .1       0
Bank Sta=574.1,589.1
XS Rating Curve= 0 ,0
Exp/Cntr=0.3,0.1

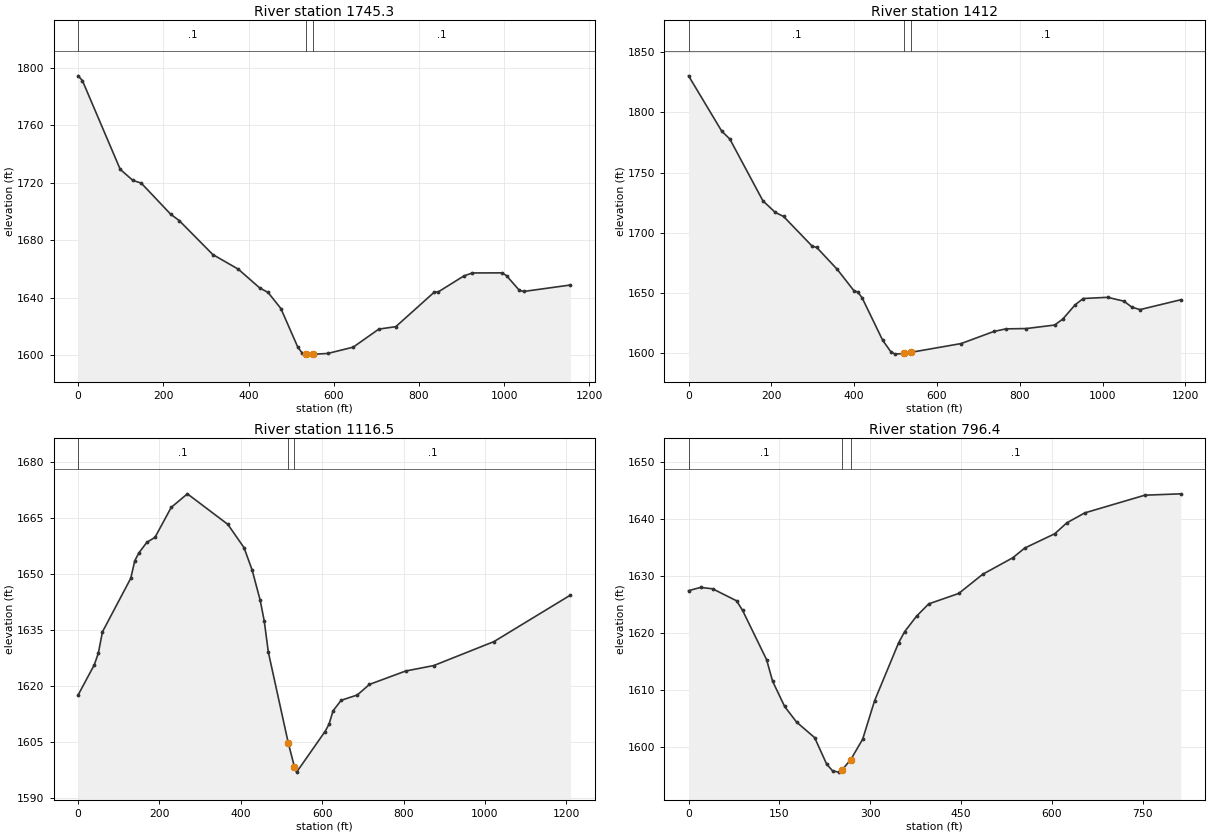
Type RM Length L Ch R = 1 ,1745.3  ,336.5,333.2,335.7
XS GIS Cut Line= 3
     1872601.527      319549.032     1872778.474      319834.661
     1873059.503      320604.785
#Sta/Elev= 30
       0 1794.43     9.9 1791.16    98.8 1729.35   128.5 1721.69   148.2 1719.78
   217.4  1698.1   237.2 1693.76   316.2 1670.08     376 1659.92     426 1646.93
     446 1643.69     476 1632.54     516  1605.5     526 1601.56   535.9 1600.89
   550.9 1600.81   555.9  1600.8   585.9 1601.25   645.9 1605.66   705.9  1618.2
   745.9 1619.92   835.9 1643.85   845.9 1644.16   905.9 1655.24   925.8 1657.28
   995.8 1657.35  1005.8  1655.4  1035.8 1645.26  1045.8 1644.38  1155.8 1648.89
#Mann= 3 , 0 , 0
       0      .1       0   535.9    .045       0   550.9      .1       0
Bank Sta=535.9,550.9
XS Rating Curve= 0 ,0
Exp/Cntr=0.3,0.1

Type RM Length L Ch R = 1 ,1412    ,314.7,295.5,276.4
XS GIS Cut Line= 3
     1872337.368      319651.964     1872658.322      320249.431
     1872996.407      320632.038
#Sta/Elev= 30
       0 1830.39    79.8 1784.63    99.7  1777.9   179.5  1726.7   209.4 1717.02
   229.4  1713.7   299.2 1688.77   309.2 1688.08   359.1 1669.75     399 1652.21
   408.9 1650.81   418.9 1646.31   468.8 1610.92   488.7 1601.28   498.7 1599.42
   521.1    1600   536.1 1600.86   658.3 1608.19   737.1 1618.21   766.6 1620.39
   815.7 1620.65   884.4 1623.58     904 1628.62   933.5  1640.3   953.1 1645.58
  1012.1 1646.56  1051.3 1643.38    1071 1638.31  1090.6 1636.39  1188.8 1644.56
#Mann= 3 , 0 , 0
       0      .1       0   521.1    .045       0   536.1      .1       0
Bank Sta=521.1,536.1
XS Rating Curve= 0 ,0
Exp/Cntr=0.3,0.1

Type RM Length L Ch R = 1 ,1116.5  ,321.6,320.1,318.7
XS GIS Cut Line= 3
     1871884.451      320201.561     1872579.318      320328.435
     1872940.804      320679.497
#Sta/Elev= 30
       0 1617.72    39.8 1625.82    49.7 1628.94    59.7 1634.61   129.3 1648.96
   139.3 1653.67   149.2 1655.76   169.1 1658.62     189 1659.94   228.8 1667.96
   268.6 1671.59   368.1 1663.41   407.9 1657.16   427.8 1651.18   447.7 1643.04
   457.6  1637.5   467.6  1629.2   516.7 1604.84   531.7 1598.49   537.2 1597.05
   606.9 1607.91   616.8 1609.86   626.8 1613.48   646.7 1616.29   686.5 1617.72
   716.2 1620.54   805.2 1624.13   874.3 1625.59  1022.5 1632.02  1210.3 1644.46
#Mann= 3 , 0 , 0
       0      .1       0   516.7    .045       0   531.7      .1       0
Bank Sta=516.7,531.7
XS Rating Curve= 0 ,0
Exp/Cntr=0.3,0.1

Type RM Length L Ch R = 1 ,796.4   ,785.7,796.2,806.7
XS GIS Cut Line= 2
     1872133.275      320583.552     1872940.804      320679.497
#Sta/Elev= 30
       0 1627.45    19.8 1628.02    39.7 1627.78    79.3 1625.67    89.2 1623.99
   128.9 1615.33   138.8 1611.55   158.7 1607.11   178.5 1604.36   208.3 1601.64
   228.1 1596.99     238  1595.8   247.9 1595.58   252.9 1595.88   267.9 1597.78
   287.6 1601.36   307.4 1608.15   347.1 1618.32     357 1620.26   376.8 1622.99
   396.7 1625.13   446.3 1626.96   485.9 1630.33   535.5 1633.22   555.4 1634.94
     605 1637.45   624.8 1639.36   654.5 1641.11   753.7 1644.22   813.2 1644.46
#Mann= 3 , 0 , 0
       0      .1       0   252.9    .045       0   267.9      .1       0
Bank Sta=252.9,267.9
XS Rating Curve= 0 ,0
Exp/Cntr=0.3,0.1

Chan Stop Cuts=-1
Use User Specified Reach Order=0
Composite Channel Slope=5